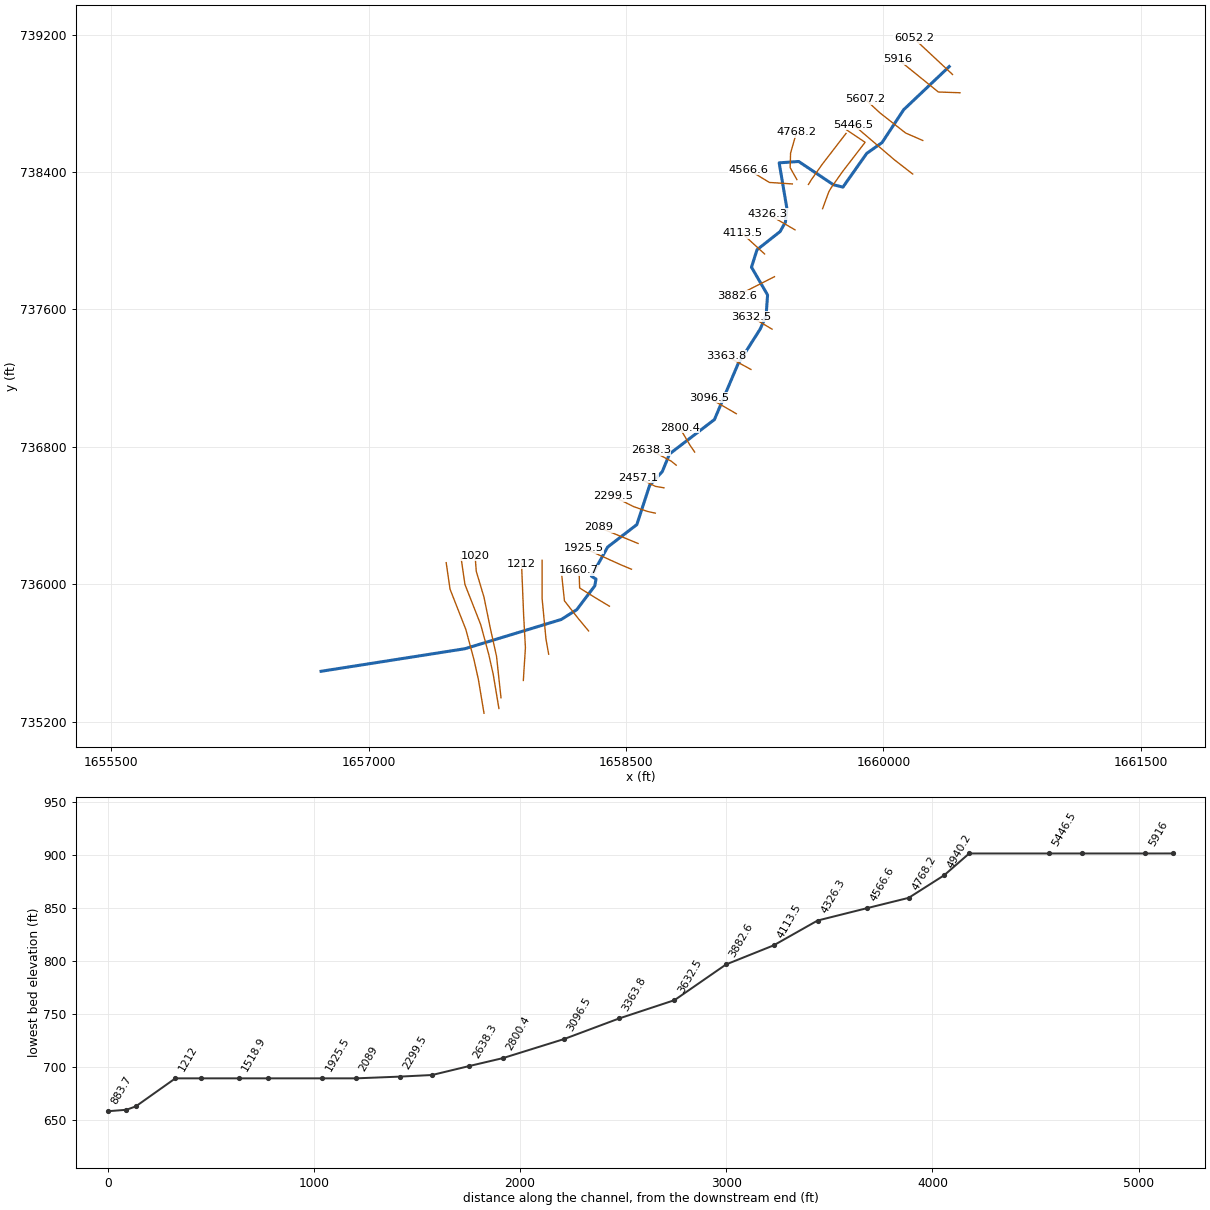
--- DEEPGUTRN.prj (project) ---

Proj Title=DEEPGUTRN
Current Plan=p01
Default Exp/Contr=0,0
English Units
Geom File=g01
Flow File=f01
Plan File=p01
BEGIN DESCRIPTION:
END DESCRIPTION:
DSS Export Rating Curves= 0
DSS Export Rating Curve Sorted= 0
DSS Export Volume Flow Curves= 0
DXF Filename=..\..\..\..\..\Engineering\Hydraulics\DEEPGUTRN\DEEPGUTRN.
DXF OffsetX= 0
DXF OffsetY= 0
DXF ScaleX= 0
DXF ScaleY= 0

--- DEEPGUTRN.p01 (plan) ---

Plan Title=Floodplain
Program Version=4.00
Geom File=g01
Flow File=f01
K Sum by GR=0
Std Step Tol=0.01
Critical Tol=0.01
Num of Std Step Trials=20
Max Error Tol=0.3
Flow Tol Ratio=0.001
Split Flow NTrial=30
Split Flow Tol=0.02
Split Flow Ratio=0.02
Log Output Level=0
Friction Slope Method=1
Unsteady Friction Slope Method=2
Unsteady Bridges Friction Slope Method=1
Global Log Level=0
CheckData=False
Run HTab=0
Run UNet=0
Run PostProcess=0
UNET Theta=0
UNET Theta Warmup=0
UNET ZTol=0
UNET ZSATol=0
UNET MxIter=0
UNET MaxInSteps=0
UNET DtIC=0
UNET DtMin=0
UNET MaxCRTS=0
UNET WFStab=0
UNET SFStab=0
UNET WFX=0
UNET SFX=0
UNET DSS MLevel=0
UNET DZMax Abort=0
UNET Convert EG Bridges=0
UNET Use Existing IB Tables=0
UNET Froude Limit=0
UNET Froude Power=0
Write IC File=0
Echo Input=False
Echo Output=False
Write Detailed=0

--- DEEPGUTRN.f01 (steady flow) ---

Flow Title=NFF Regression Equation
Program Version=4.10
Number of Profiles= 1
Profile Names=P100yr
River Rch & RM=DEEPGUTRN,Main            ,6052.2
1031.719
River Rch & RM=DEEPGUTRN,Main            ,1334.8
1100.527
Boundary for River Rch & Prof#=DEEPGUTRN,Main            , 1
Up Type= 0
Dn Type= 3
Dn Slope=0.05
DSS Import GetInterval= 0
DSS Import GetPeak= 0
DSS Import FillOption= 0

--- DEEPGUTRN.g01 (geometry) ---

Geom Title=USGS 10m DEM
Program Version=4.10

River Reach=DEEPGUTRN       ,Main
Reach XY= 30
     1660383.562      739014.093     1660117.869      738762.549
     1659991.954      738571.266     1659902.604      738508.407
     1659763.904      738312.015     1659708.465      738325.808
     1659506.208      738461.225     1659392.358      738453.329
     1659436.764       738191.26     1659428.951      738108.794
     1659397.701      738053.239     1659263.153      737947.336
     1659231.034      737845.774     1659324.784      737684.315
     1659316.104      737562.787     1659280.999      737484.378
     1659152.909      737283.274     1659015.154      736958.987
      1658753.17      736758.534     1658711.389      736656.185
     1658637.347      736575.432     1658562.886      736347.269
     1658392.617      736216.525     1658297.909      736047.129
     1658324.858      736030.189     1658317.929       735990.92
      1658212.88      735852.093     1658122.697      735795.088
     1657561.388      735624.739     1656722.804      735493.354

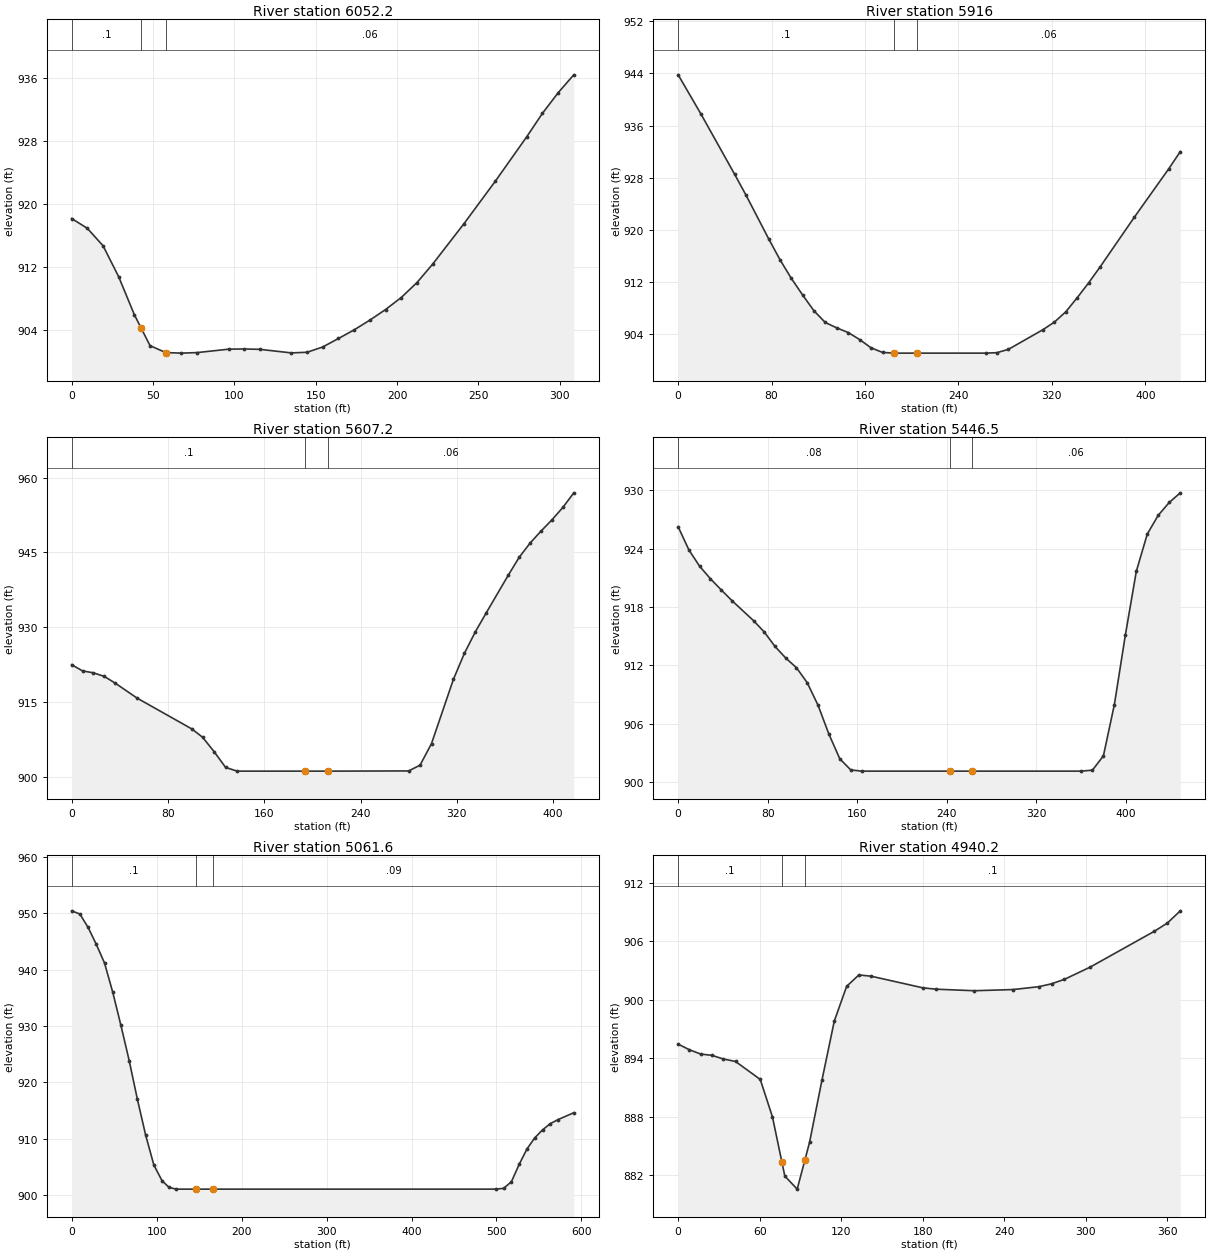
Type RM Length L Ch R = 1 ,6052.2  ,134.6,136.2,137.8
XS GIS Cut Line= 2
      1660402.72      738967.726     1660177.025       739178.23
#Sta/Elev= 29
       0   918.2     9.6  916.96    19.3  914.74    28.9  910.81    38.6  905.96
   42.78904.2581    48.2  902.05    57.9  901.18    67.5  901.11    77.2  901.18
    96.4  901.61   106.1  901.64   115.7  901.59     135  901.14   144.7  901.22
   154.3  901.89     164  902.97   173.6  904.06   183.2  905.29   192.9  906.64
   202.5  908.16   212.2  910.06   221.8  912.39   241.1  917.54   260.4  922.94
   279.7  928.58   289.3  931.54     299  934.17   308.6  936.44
#Mann= 3 , 0 , 0
       0      .1       0   42.78    .045       0    57.9     .06       0
Bank Sta=42.78,57.9
XS Rating Curve= 0 ,0
Exp/Cntr=0.3,0.1

Type RM Length L Ch R = 1 ,5916    ,308.4,308.8,309.1
XS GIS Cut Line= 3
     1660446.122       738861.39     1660320.254       738865.73
     1660083.709      739056.702
#Sta/Elev= 29
       0  943.79    19.4  937.81    48.4  928.52    58.1  925.33    77.5  918.63
    87.2  915.43    96.9  912.56   106.6  910.01   116.2  907.61   125.9  905.81
   135.8  904.97   145.6  904.26   155.4  903.18   165.2  901.91     175  901.21
   184.8   901.1   204.4   901.1   263.2   901.1     273  901.17   282.8  901.68
   312.3  904.69   322.1  905.85   331.9  907.43   341.7   909.6   351.5  911.88
   361.3  914.32   390.7  921.97   420.2   929.4     430  932.02
#Mann= 3 , 0 , 0
       0      .1       0   184.8    .045       0   204.4     .06       0
Bank Sta=184.8,204.4
XS Rating Curve= 0 ,0
Exp/Cntr=0.3,0.1

Type RM Length L Ch R = 1 ,5607.2  ,161.7,160.7,159.7
XS GIS Cut Line= 4
     1660229.108      738583.612     1660129.282      738627.015
     1659979.542      738744.202     1659892.737      738824.497
#Sta/Elev= 27
       0  922.47     9.1  921.22    18.1  920.84    27.2  920.11    36.3  918.75
    54.4  915.76    99.8  909.58   108.8   907.9   118.4     905   127.9  901.85
   137.4   901.1     194   901.1   213.4   901.1     280  901.14   289.5   902.3
     299  906.64   317.2  919.53   326.3  924.75   335.4  929.06   344.5   932.9
   362.7  940.41   371.8  944.02   380.9  946.89     390   949.3     399  951.54
   408.2  954.07   417.2  956.98
#Mann= 3 , 0 , 0
       0      .1       0     194    .045       0   213.4     .06       0
Bank Sta=194,213.4
XS Rating Curve= 0 ,0
Exp/Cntr=0.3,0.1

Type RM Length L Ch R = 1 ,5446.5  ,418.6,384.9,346.4
XS GIS Cut Line= 3
     1660170.515      738388.299     1660064.178      738470.765
     1659825.463      738674.758
#Sta/Elev= 29
       0  926.24     9.6  923.86    19.2  922.18    28.8   920.9    38.4  919.76
    48.1  918.64    67.3  916.59    76.9  915.42    86.5  913.93    96.1  912.74
   105.7  911.74   115.3   910.2     125  907.87   134.6  904.92   144.4  902.37
   154.2  901.22     164   901.1   242.5   901.1   262.2   901.1   360.3   901.1
   370.1   901.2   379.9  902.67   389.7  907.95   399.5   915.1   409.3  921.66
   419.1   925.5   428.9  927.43   438.8  928.76   448.6  929.74
#Mann= 3 , 0 , 0
       0     .08       0   242.5    .045       0   262.2     .06       0
Bank Sta=242.5,262.2
XS Rating Curve= 0 ,0
Exp/Cntr=0.3,0.1

Type RM Length L Ch R = 1 ,5061.6  ,121.7,121.4,121.3
XS GIS Cut Line= 6
     1659645.341      738186.476     1659682.233      738286.303
     1659699.595      738314.515     1659762.529       738403.49
     1659893.174      738572.921       1659786.4      738644.376
#Sta/Elev= 26
       0  950.42     9.7  949.85    19.4  947.47      29  944.48    38.7  941.17
    48.4  935.98      58  930.11    67.7  923.89    77.4     917    87.1  910.68
    96.8  905.35   106.4  902.59   114.7   901.4     123   901.1   146.4   901.1
   166.8   901.1   499.2   901.1   508.4  901.24   517.6  902.41   526.7  905.48
   535.9  908.22   545.1  910.19   554.2   911.6   563.4  912.71   572.6  913.43
     591  914.64
#Mann= 3 , 0 , 0
       0      .1       0   146.4    .045       0   166.8     .09       0
Bank Sta=146.4,166.8
XS Rating Curve= 0 ,0
Exp/Cntr=0.3,0.1

Type RM Length L Ch R = 1 ,4940.2  ,158.3,172,185
XS GIS Cut Line= 4
     1659562.876      738327.535     1659580.237      738355.747
     1659643.171      738444.723      1659782.06      738624.844
#Sta/Elev= 29
       0  895.43     8.3  894.85    16.6  894.41    24.8  894.28    33.1  893.91
    42.2  893.65    60.4  891.81    69.4  887.96    76.3 883.357    78.5  881.89
    87.6  880.55    93.2 883.501    96.7  885.35   105.8  891.71   114.9  897.79
     124  901.36     133  902.53   142.1   902.4     180  901.21   189.5  901.07
   217.9  900.91   246.4  901.03   265.3  901.32   274.8  901.62   284.3  902.08
   303.2  903.33   350.6  907.02   360.1  907.86   369.6  909.11
#Mann= 3 , 0 , 0
       0      .1       0    76.3    .045       0    93.2      .1       0
Bank Sta=76.3,93.2
XS Rating Curve= 0 ,0
Exp/Cntr=0.3,0.1

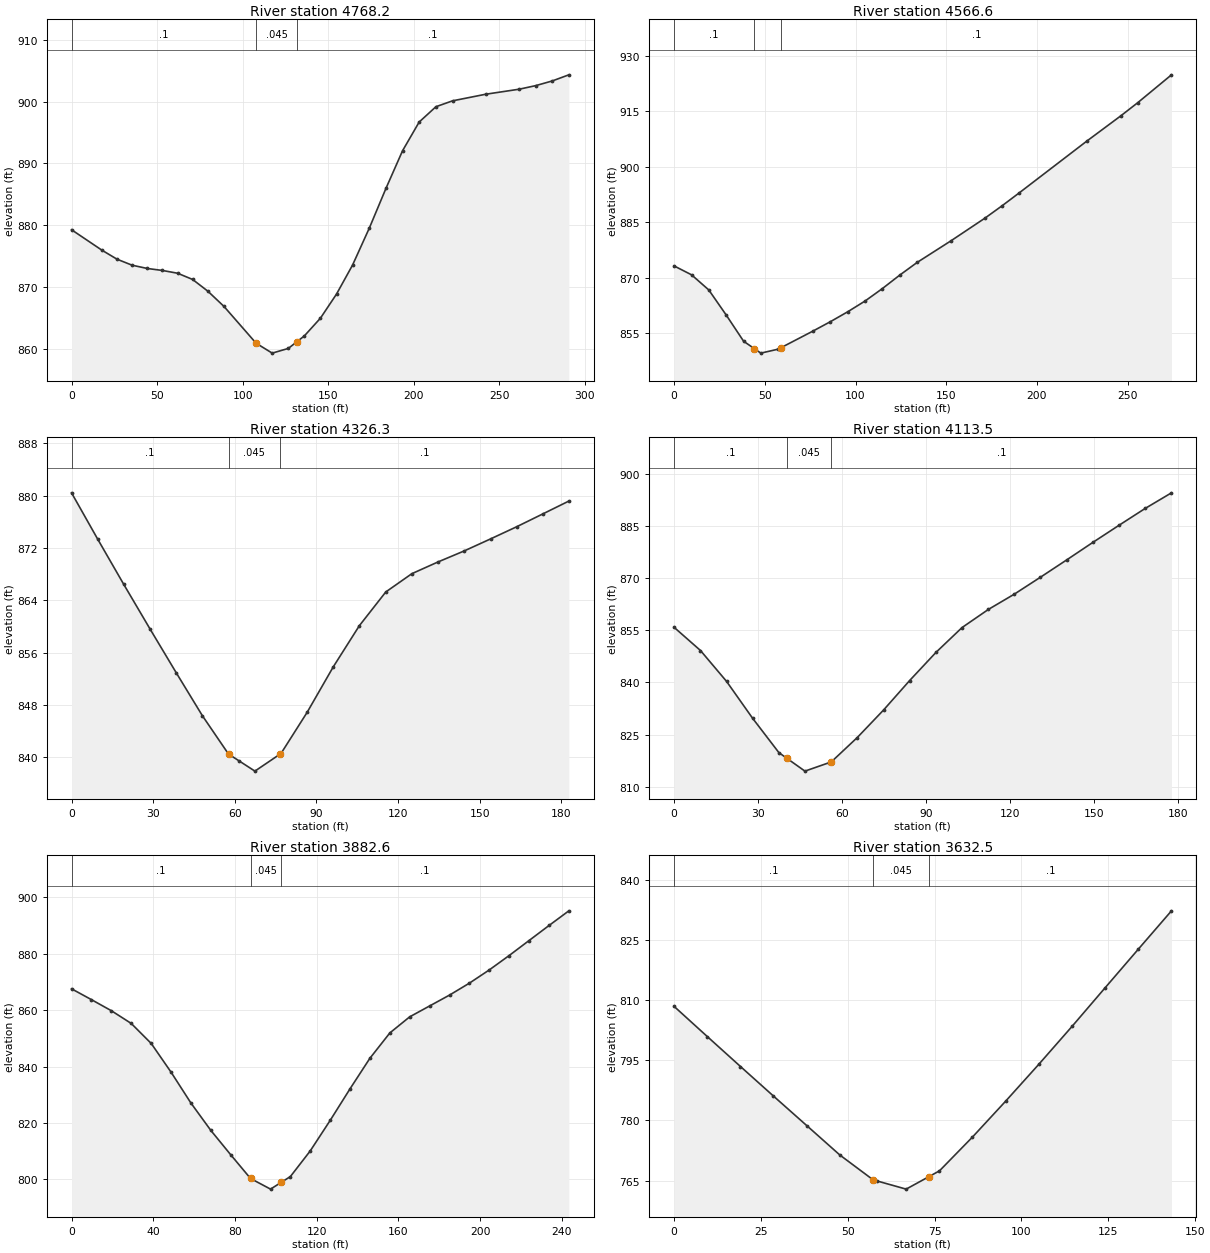
Type RM Length L Ch R = 1 ,4768.2  ,163,201.6,236
XS GIS Cut Line= 4
     1659495.602      738355.747     1659456.539      738425.192
     1659458.709      738509.827     1659493.431      738631.355
#Sta/Elev= 29
       0  879.25    17.7  875.95    26.6  874.48    35.4  873.51    44.3  872.98
    53.1  872.66      62  872.21    70.8   871.2    79.7   869.3    89.1  866.84
   107.9  860.88   117.3  859.28   126.7  860.04   131.9  861.16   136.1  862.07
   145.5  864.94   154.9  868.84   164.3  873.55   174.1  879.54   183.8  885.95
   193.5  892.04   203.2  896.68     213  899.16   222.7  900.11   242.1  901.18
   261.6  901.99   271.3  902.57     281  903.33   290.7  904.32
#Mann= 3 , 0 , 0
       0      .1       0   107.9    .045       0   131.9      .1       0
Bank Sta=107.9,131.9
XS Rating Curve= 0 ,0
Exp/Cntr=0.3,0.1

Type RM Length L Ch R = 1 ,4566.6  ,250.4,240.3,229.2
XS GIS Cut Line= 3
     1659469.126      738330.574     1659335.445      738339.254
     1659215.654      738412.171
#Sta/Elev= 24
       0  873.15     9.6  870.75    19.1  866.66    28.7  859.88    38.3  852.79
    44.1  850.83    47.8  849.58    57.4  850.66    59.1   851.1    76.6  855.56
    86.1  858.07    95.7  860.76   105.3  863.68   114.8  867.03   124.4  870.68
     134  874.11   152.7  879.97   171.4  886.09   180.7  889.38   190.1  892.85
   227.4  906.86   246.2  913.71   255.5  917.25   274.2  924.82
#Mann= 3 , 0 , 0
       0      .1       0    44.1    .045       0    59.1      .1       0
Bank Sta=44.1,59.1
XS Rating Curve= 0 ,0
Exp/Cntr=0.3,0.1

Type RM Length L Ch R = 1 ,4326.3  ,217.4,212.8,207.9
XS GIS Cut Line= 2
     1659484.751      738063.212     1659326.765      738155.226
#Sta/Elev= 22
       0  880.44     9.6  873.37    19.2  866.44    28.9  859.59    38.5  852.92
    48.1  846.36    57.7   840.5    61.5  839.48    67.4  837.89    76.5  840.45
      77  840.59    86.6  846.88    96.2  853.83   105.8  860.13   115.5  865.28
   125.1  868.08   134.7  869.87   144.3  871.55     154  873.39   163.6  875.25
   173.2  877.21   182.8  879.18
#Mann= 3 , 0 , 0
       0      .1       0    57.7    .045       0    76.5      .1       0
Bank Sta=57.7,76.5
XS Rating Curve= 0 ,0
Exp/Cntr=0.3,0.1

Type RM Length L Ch R = 1 ,4113.5  ,202.7,230.9,257.8
XS GIS Cut Line= 2
     1659307.667      737922.587     1659176.591      738042.379
#Sta/Elev= 22
       0  855.84     9.4  849.19    18.7  840.33      28  829.73    37.4  819.84
    40.3  818.18    46.7  814.52    55.3  816.94    56.1  817.16    65.4  824.18
    74.8   832.1    84.1  840.56    93.5  848.65   102.8  855.78   112.2  860.99
   121.5   865.4   130.8  870.25   140.2  875.24   149.5  880.25   158.9   885.2
   168.2  890.02   177.6  894.51
#Mann= 3 , 0 , 0
       0      .1       0    40.3    .045       0    56.1      .1       0
Bank Sta=40.3,56.1
XS Rating Curve= 0 ,0
Exp/Cntr=0.3,0.1

Type RM Length L Ch R = 1 ,3882.6  ,272.6,250.1,226.7
XS GIS Cut Line= 2
     1659364.959      737790.643     1659147.945        737680.4
#Sta/Elev= 27
       0   867.6     9.7  863.77    19.5  859.82    29.2  855.32      39  848.21
    48.7  838.04    58.4  827.11    68.2  817.34    77.9  808.73    87.6  800.31
    97.4  796.53   102.6  798.92   107.1  800.98   116.8  810.06   126.6  820.93
   136.3  832.12     146  842.93   155.8  851.95   165.5  857.65   175.3  861.53
     185  865.37   194.7  869.59   204.5  874.32   214.2  879.41   223.9  884.71
   233.7  890.06   243.4  895.26
#Mann= 3 , 0 , 0
       0      .1       0    87.6    .045       0   102.6      .1       0
Bank Sta=87.6,102.6
XS Rating Curve= 0 ,0
Exp/Cntr=0.3,0.1

Type RM Length L Ch R = 1 ,3632.5  ,267.8,268.7,269.5
XS GIS Cut Line= 2
      1659351.07      737485.087     1659227.806      737558.004
#Sta/Elev= 18
       0   808.4     9.6  800.85    19.1  793.43    28.6  786.06    38.2  778.69
    47.7  771.38    57.3  765.18    58.4  764.91    66.8  762.87    73.4     766
    76.4  767.43    85.9  775.85    95.5  784.84     105  793.98   114.6  803.46
   124.1  813.06   133.7  822.72   143.2  832.23
#Mann= 3 , 0 , 0
       0      .1       0    57.3    .045       0    73.4      .1       0
Bank Sta=57.3,73.4
XS Rating Curve= 0 ,0
Exp/Cntr=0.3,0.1

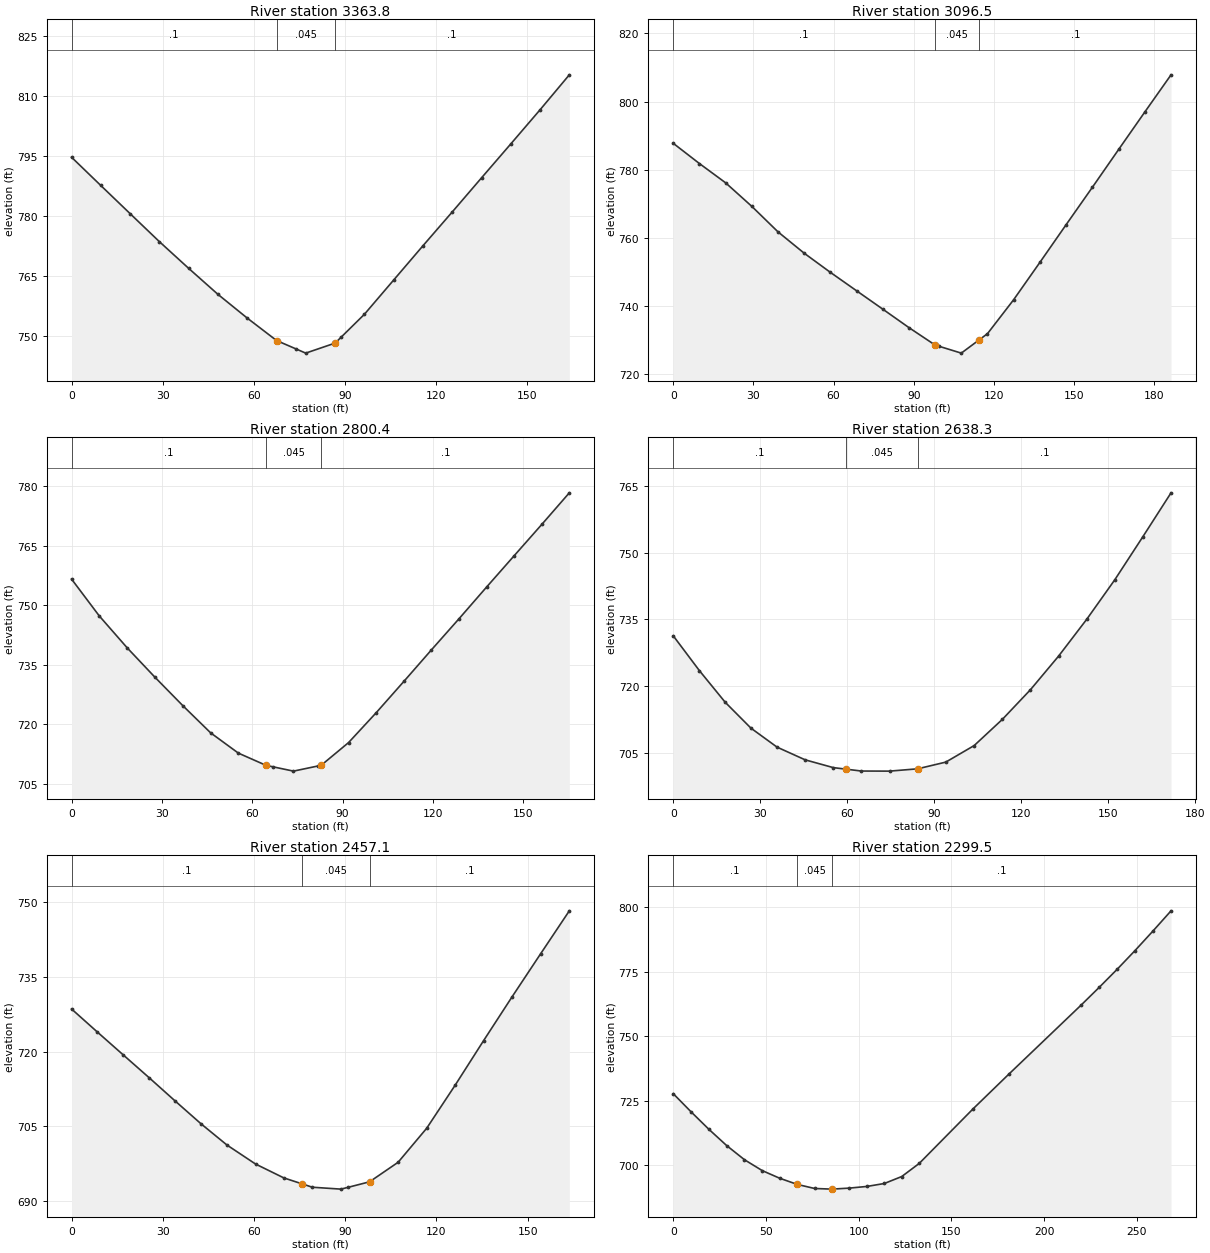
Type RM Length L Ch R = 1 ,3363.8  ,267.9,267.3,266.7
XS GIS Cut Line= 2
     1659227.806      737250.712     1659083.709      737328.837
#Sta/Elev= 20
       0  794.71     9.6  787.65    19.3  780.56    28.9  773.57    38.6  766.84
    48.2  760.35    57.8  754.43    67.5  748.78    73.8  746.71    77.1  745.62
    86.8  748.14    88.8  749.64    96.4  755.33   106.1  763.97   115.7  772.52
   125.4  781.04     135  789.55   144.6  798.02   154.3  806.63   163.9  815.36
#Mann= 3 , 0 , 0
       0      .1       0    67.5    .045       0    86.8      .1       0
Bank Sta=67.5,86.8
XS Rating Curve= 0 ,0
Exp/Cntr=0.3,0.1

Type RM Length L Ch R = 1 ,3096.5  ,307.6,296.1,284.3
XS GIS Cut Line= 2
     1659142.737        736992.9     1658981.279      737085.782
#Sta/Elev= 22
       0  787.75     9.8  781.81    19.6  776.16    29.4  769.25    39.2  761.77
      49  755.51    58.8  749.89    68.6  744.49    78.4   739.1    88.2  733.68
      98  728.56    99.6  728.17   107.8  726.19   114.6  730.15   117.6   731.9
   127.4  741.87   137.2   752.8     147  763.84   156.9   774.9   166.7  785.96
   176.5  796.96   186.3  807.85
#Mann= 3 , 0 , 0
       0      .1       0      98    .045       0   114.6      .1       0
Bank Sta=98,114.6
XS Rating Curve= 0 ,0
Exp/Cntr=0.3,0.1

Type RM Length L Ch R = 1 ,2800.4  ,149.8,162.1,174.4
XS GIS Cut Line= 3
     1658899.681       736769.81      1658873.64      736808.004
     1658812.876      736910.435
#Sta/Elev= 21
       0   756.6     9.2  747.33    18.5  739.27    27.7  731.89      37   724.7
    46.2  717.89    55.4  712.79    64.6  709.71    66.8  709.36    73.7  708.26
    81.8  709.55    82.9  709.73      92  715.45   101.2  722.99   110.4  730.88
   119.5  738.77   128.7  746.64   137.8  754.57     147  762.49   156.2  770.39
   165.3  778.31
#Mann= 3 , 0 , 0
       0      .1       0    64.6    .045       0    82.9      .1       0
Bank Sta=64.6,82.9
XS Rating Curve= 0 ,0
Exp/Cntr=0.3,0.1

Type RM Length L Ch R = 1 ,2638.3  ,180.4,181.2,182
XS GIS Cut Line= 3
     1658792.042      736693.421     1658764.265       736715.99
     1658644.473      736780.226
#Sta/Elev= 20
       0   731.3       9  723.48    17.9  716.36    26.8  710.52    35.8  706.25
    45.5  703.39    55.2  701.64    59.6  701.29    64.9  700.87    74.6  700.85
    84.3  701.37      94  702.88   103.8  706.61   113.5  712.49   123.2  719.17
   132.9  726.73   142.6  735.01   152.3  743.92     162  753.63   171.7  763.49
#Mann= 3 , 0 , 0
       0      .1       0    59.6    .045       0    84.3      .1       0
Bank Sta=59.6,84.3
XS Rating Curve= 0 ,0
Exp/Cntr=0.3,0.1

Type RM Length L Ch R = 1 ,2457.1  ,154.7,157.6,160.5
XS GIS Cut Line= 3
     1658720.862      736561.476     1658670.515      736570.157
      1658569.82      736620.504
#Sta/Elev= 21
       0  728.56     8.5  723.92      17  719.33    25.6   714.7    34.1  710.05
    42.6  705.47    51.1  701.22    60.5   697.4    69.8  694.61    75.8  693.41
    79.2  692.73    88.6  692.35    90.8  692.69      98  693.82   107.4  697.75
   116.8  704.59   126.1  713.19   135.5  722.19   144.9  731.03   154.3  739.69
   163.7  748.29
#Mann= 3 , 0 , 0
       0      .1       0    75.8    .045       0      98      .1       0
Bank Sta=75.8,98
XS Rating Curve= 0 ,0
Exp/Cntr=0.3,0.1

Type RM Length L Ch R = 1 ,2299.5  ,210.7,210.6,212.7
XS GIS Cut Line= 4
     1658670.515      736413.907      1658623.64      736424.324
     1658543.779      736452.101     1658422.251      736512.865
#Sta/Elev= 23
       0  727.77     9.6  720.75    19.2  713.99    28.8  707.68    38.4   702.2
      48  697.98    57.4  695.03    66.8  692.66    76.2  691.07    85.6  690.82
      95  691.22   104.4  691.86   113.8     693   123.2   695.7   132.6  700.76
   161.7  721.94   181.1  735.45   219.9  762.07   229.6   768.9   239.3  775.91
     249  783.21   258.7   790.8   268.4  798.58
#Mann= 3 , 0 , 0
       0      .1       0    66.8    .045       0    85.6      .1       0
Bank Sta=66.8,85.6
XS Rating Curve= 0 ,0
Exp/Cntr=0.3,0.1

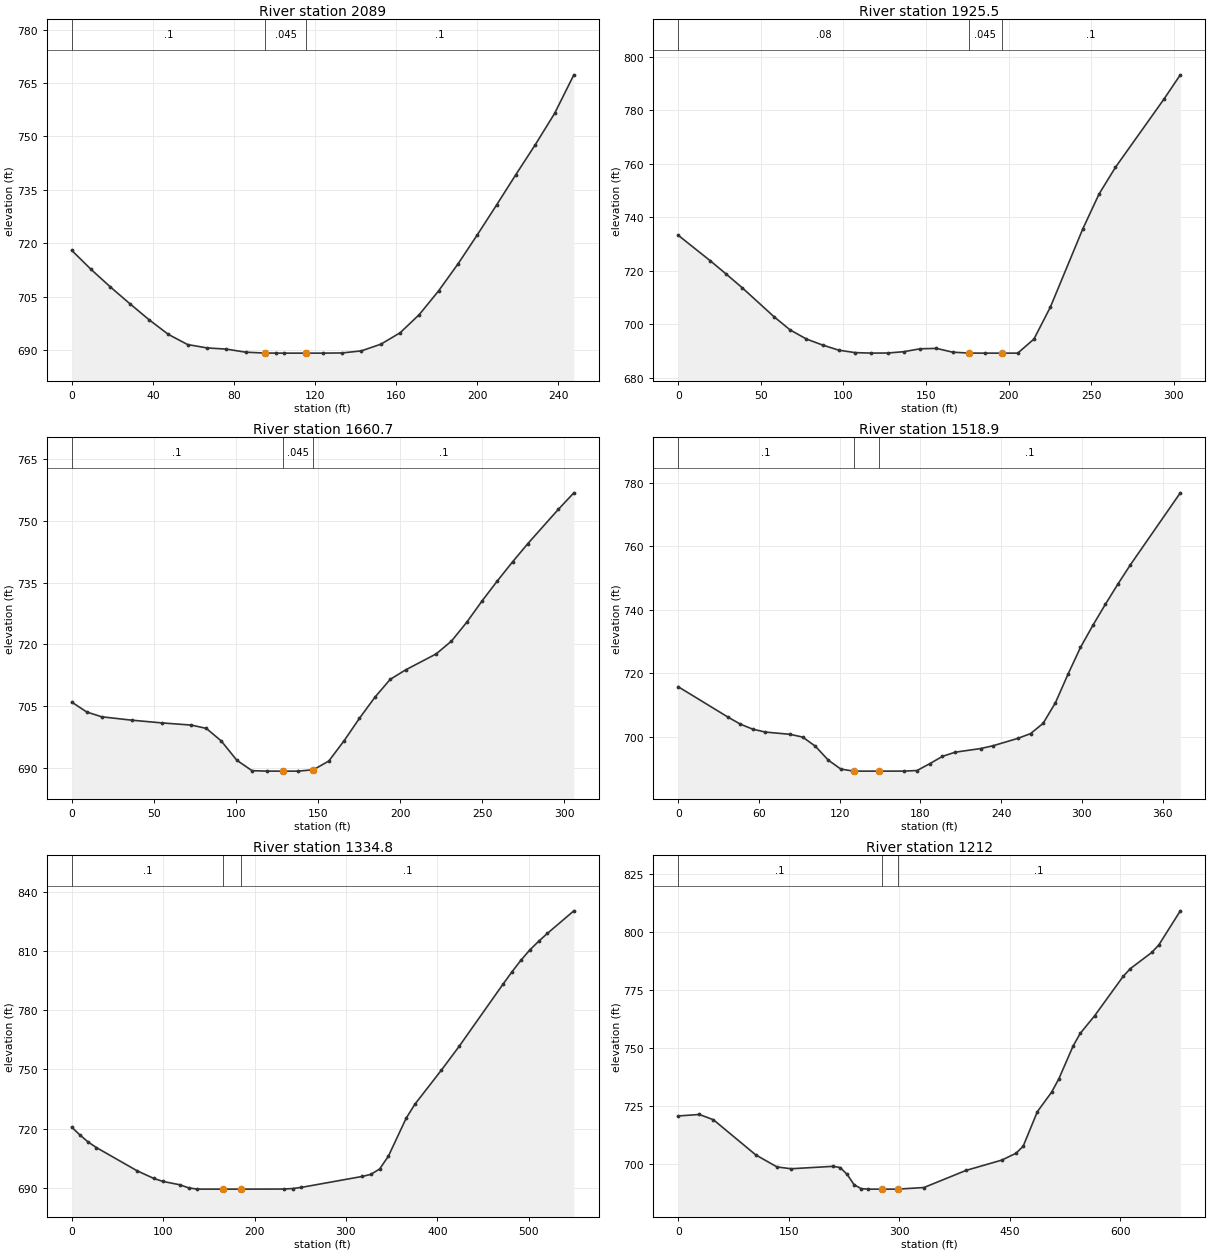
Type RM Length L Ch R = 1 ,2089    ,165.4,163.5,159.1
XS GIS Cut Line= 2
      1658569.82      736237.692     1658340.654      736331.442
#Sta/Elev= 29
       0  718.03     9.5   712.7      19  707.79    28.6  703.09    38.1  698.58
    47.6  694.47    57.1  691.61    66.7  690.66    76.2  690.33    85.7  689.47
    95.2  689.22   100.7  689.21   104.8   689.2   114.3   689.2   115.7   689.2
   123.8   689.2   133.3  689.25   142.8  689.83   152.4   691.7   161.9   694.9
   171.4  700.03   180.9  706.67   190.5  714.26     200   722.4   209.5  730.77
     219  739.29   228.6   747.7   238.1  756.45   247.6  767.29
#Mann= 3 , 0 , 0
       0      .1       0    95.2    .045       0   115.7      .1       0
Bank Sta=95.2,115.7
XS Rating Curve= 0 ,0
Exp/Cntr=0.3,0.1

Type RM Length L Ch R = 1 ,1925.5  ,263.1,264.9,264
XS GIS Cut Line= 3
     1658531.626      736087.518     1658469.126       736113.56
     1658253.848      736210.782
#Sta/Elev= 27
       0  733.23    19.4   723.7      29  718.75    38.7  713.64      58  702.79
    67.7  697.88    77.6  694.47    87.4  692.22    97.2   690.3   107.1  689.39
   116.9  689.21   126.8  689.24   136.6  689.74   146.4  690.82   156.3  690.97
   166.1  689.56     176  689.22   185.8   689.2   195.7   689.2   205.5   689.2
   215.3  694.45   225.2  706.33   244.9  735.65   254.7  748.62   264.6  758.58
   294.1  784.18   303.9  793.16
#Mann= 3 , 0 , 0
       0     .08       0     176    .045       0   195.7      .1       0
Bank Sta=176,195.7
XS Rating Curve= 0 ,0
Exp/Cntr=0.3,0.1

Type RM Length L Ch R = 1 ,1660.7  ,149.2,141.7,133.2
XS GIS Cut Line= 4
     1658403.154       735872.24     1658325.029      735919.115
     1658229.542      735978.143      1658226.07      736080.574
#Sta/Elev= 30
       0  705.96     9.1  703.57    18.2   702.4    36.4  701.58    54.7  700.92
    72.9  700.38      82  699.58    91.1  696.52   100.5  691.87   109.8  689.31
   119.2   689.2   128.5   689.2   137.9   689.2   146.8  689.52   147.2  689.53
   156.6  691.65     166  696.62   175.3  702.05   184.7  707.15     194  711.49
   203.4  713.79     222  717.67   231.3  720.77   240.6  725.34     250  730.55
   259.3  735.41   268.6  740.05   277.9  744.48   296.5  752.81   305.9   756.8
#Mann= 3 , 0 , 0
       0      .1       0   128.5    .045       0   146.8      .1       0
Bank Sta=128.5,146.8
XS Rating Curve= 0 ,0
Exp/Cntr=0.3,0.1

Type RM Length L Ch R = 1 ,1518.9  ,196.8,184.1,171
XS GIS Cut Line= 4
     1658281.626      735728.143     1658222.598      735799.324
     1658141.001       735903.49     1658125.376       736051.06
#Sta/Elev= 30
       0  715.76      37   706.2    46.2  703.98    55.5  702.39    64.7   701.5
    83.2  700.78    92.5  699.91   101.9  697.06   111.4  692.71   120.8  689.86
   130.3   689.2   149.2   689.2   168.1  689.21   177.5  689.39     187  691.55
   196.4  693.85   205.9  695.16   224.8  696.31   234.1   697.2   252.6  699.53
   261.9  701.02   271.2  704.23   280.4  710.75   289.7  719.69     299  728.14
   308.3  735.17   317.5  741.72   326.8  748.07   336.1  754.15   373.2   776.8
#Mann= 3 , 0 , 0
       0      .1       0   130.3    .045       0   149.2      .1       0
Bank Sta=130.3,149.2
XS Rating Curve= 0 ,0
Exp/Cntr=0.3,0.1

Type RM Length L Ch R = 1 ,1334.8  ,124.2,122.7,122.2
XS GIS Cut Line= 4
     1658048.987      735592.726     1658033.362      735681.268
     1658010.792      735917.379     1658010.792      736139.601
#Sta/Elev= 30
       0  720.68       9  716.68      18  713.11      27  710.31    71.9  698.41
    89.9  694.61    99.4  693.15   118.4  691.39   127.9  689.84   137.4   689.2
   165.8   689.2   184.8   689.2   232.2  689.24   241.7   689.5   251.2  690.09
   317.6  695.63   327.1  696.68   336.8  699.42   346.4  705.94   365.8  725.19
   375.4  732.35   404.4  749.66   423.7  761.67     472  793.46   481.7  799.65
   491.4   805.5     501  810.66   510.7  815.07   520.3  819.11   549.3  830.59
#Mann= 3 , 0 , 0
       0      .1       0   165.8    .045       0   184.8      .1       0
Bank Sta=165.8,184.8
XS Rating Curve= 0 ,0
Exp/Cntr=0.3,0.1

Type RM Length L Ch R = 1 ,1212    ,187.9,192,195.4
XS GIS Cut Line= 4
     1657901.417      735439.949      1657913.57      735630.921
     1657903.154      735820.157     1657891.001      736120.504
#Sta/Elev= 30
       0  720.73    28.7  721.37    47.8  719.09   105.2  703.96     134  698.77
   153.1  697.98   210.3  699.03   219.8  698.51   229.3  695.53   238.7  691.11
   248.2  689.41   257.7   689.2   276.6   689.2   297.8   689.2   333.5  689.89
   390.6  697.26   439.1   701.7   458.4  704.64   468.2  707.68   487.5   722.6
   506.9  731.03   516.6  736.71     536  750.88   545.7  756.34   565.1  763.86
   603.9  780.86   613.6   784.2   642.7  791.17   652.4  794.45   681.5  809.12
#Mann= 3 , 0 , 0
       0      .1       0   276.6    .045       0   297.8      .1       0
Bank Sta=276.6,297.8
XS Rating Curve= 0 ,0
Exp/Cntr=0.3,0.1

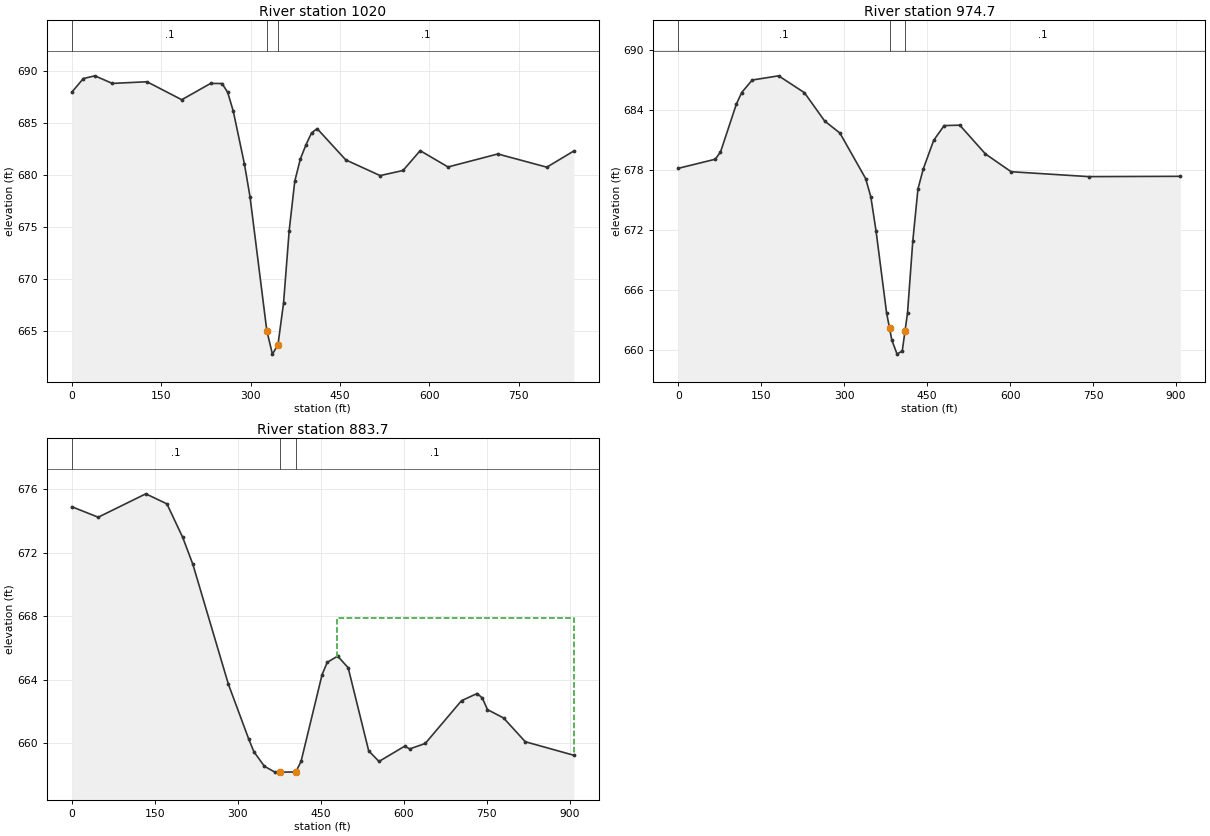
Type RM Length L Ch R = 1 ,1020    ,44.2,45.3,46.3
XS GIS Cut Line= 6
     1657771.209      735339.254     1657745.167      735580.574
     1657708.709      735745.504     1657672.251      735924.324
     1657627.112      736075.365     1657620.167      736165.643
#Sta/Elev= 30
       0  687.96    19.4  689.28    38.8  689.54      68  688.81   126.2  688.97
   184.5  687.24     233  688.81   252.1   688.8   261.5  687.96   270.9  686.15
   289.6  681.07     299  677.92   327.2  665.02   336.6  662.76   345.9  663.65
   355.3  667.68   364.7  674.62   374.1   679.4   383.5  681.54   392.9   682.9
   402.2  684.04   411.6  684.46   459.7  681.45   517.3  679.94   555.7  680.43
   584.5  682.34   631.2  680.77   714.7  682.02     797  680.75   842.3  682.31
#Mann= 3 , 0 , 0
       0      .1       0   327.2    .045       0   345.9      .1       0
Bank Sta=327.2,345.9
XS Rating Curve= 0 ,0
Exp/Cntr=0.3,0.1

Type RM Length L Ch R = 1 ,974.7   ,91.1,91.1,91.1
XS GIS Cut Line= 6
     1657759.056      735276.754      1657726.07      735474.671
     1657700.029       735590.99     1657653.154      735764.601
      1657561.14      735998.976      1657538.57       736153.49
#Sta/Elev= 30
       0  678.18    66.9  679.09    76.4  679.81   105.1  684.61   114.7  685.77
   133.8  687.02   181.5  687.44   228.2  685.75   264.8  682.91   292.3  681.71
   338.8  677.16   348.2  675.32   357.7  671.88   376.6  663.74   382.1  662.15
   386.1     661   395.6  659.58     405   659.9   410.1661.9293   414.5  663.68
     424  670.86   433.4  676.12   442.9   678.1   461.8  680.98   480.7  682.46
     509   682.5   555.4  679.62   601.8  677.84   742.2  677.35   907.7  677.38
#Mann= 3 , 0 , 0
       0      .1       0   382.1    .045       0   410.1      .1       0
Bank Sta=382.1,410.1
XS Rating Curve= 0 ,0
Exp/Cntr=0.3,0.1

Type RM Length L Ch R = 1 ,883.7   ,886.2,883.7,881.2
XS GIS Cut Line= 6
     1657672.251      735248.976     1657639.265      735446.893
     1657613.223      735563.212     1657566.348      735736.824
     1657474.334      735971.199     1657451.765      736125.712
#Sta/Elev= 30
       0  674.88    47.8  674.22   133.8  675.69     172  675.06   200.6  672.95
     219  671.25   283.2  663.72   319.8  660.29   329.3  659.48   348.2  658.57
   367.2   658.2   376.6   658.2     405  658.21   414.5  658.87   452.4  664.31
   461.8   665.1   480.7  665.49   499.7  664.76   536.8  659.54   555.4  658.87
   601.8  659.83   611.1  659.66     639     660   704.6  662.69   732.8  663.14
   742.2  662.86   751.5  662.13   780.8   661.6   819.9  660.11   907.7  659.26
#Mann= 3 , 0 , 0
       0      .1       0   376.6    .045       0     405      .1       0
#XS Ineff= 2 , 0
                          479.19          667.88
Permanent Ineff=
       F       F
Bank Sta=376.6,405
XS Rating Curve= 0 ,0
Exp/Cntr=0.3,0.1

Chan Stop Cuts=-1
Use User Specified Reach Order=0
Composite Channel Slope=5